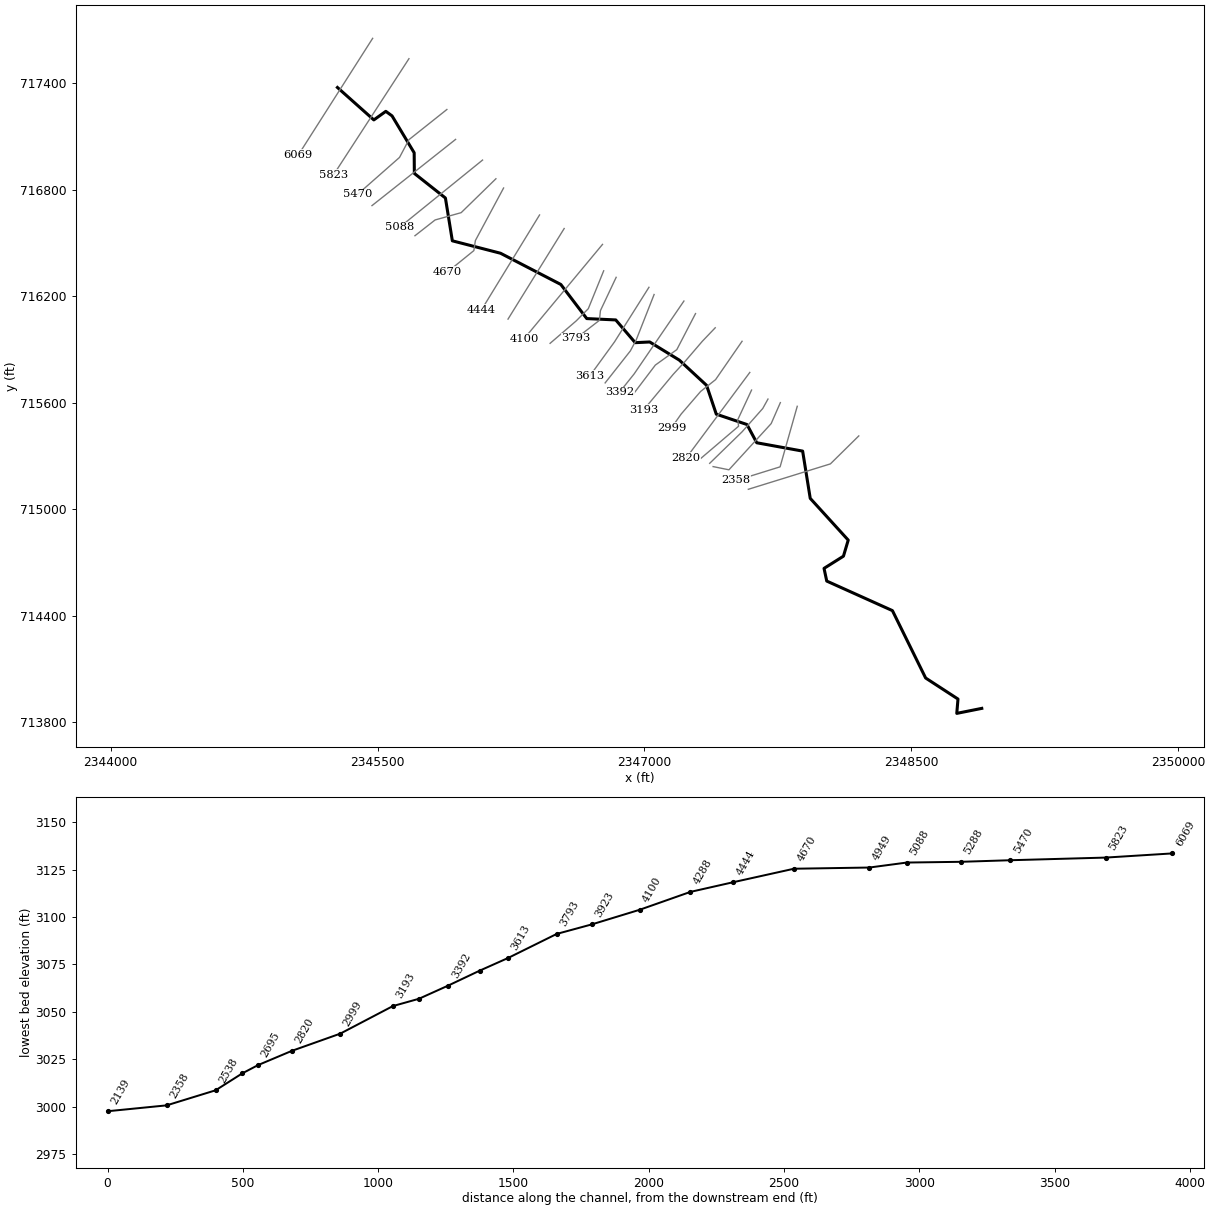
--- YELLOWCK.prj (project) ---

Proj Title=YELLOWCK
Current Plan=p01
Default Exp/Contr=0,0
English Units
Geom File=g01
Flow File=f01
Plan File=p01
BEGIN DESCRIPTION:
----------MODEL BY WOOD PLC 2022----------
AFH study: YELLOWCK
Randolph County, WV
HEC-RAS Version: RAS 6.2
Vertical Datum: NAVD88
Projection: NAD 1983 StatePlane West Virginia S FIPS 4702 (US Feet)
Terrain: 1-meter LIDAR (FEMA Region III 3DEP collected 2016-2018)
Land Use: 2019 NLCD
Hydrologic Method:
WV SIR2010-5033 regression equations
Additional Model Notes:
None
END DESCRIPTION:
DSS Export Rating Curves= 0
DSS Export Rating Curve Sorted= 0
DSS Export Volume Flow Curves= 0
DXF OffsetX= 0
DXF OffsetY= 0
DXF ScaleX= 0
DXF ScaleY= 0

--- YELLOWCK.p01 (plan) ---

Plan Title=Floodplain
Program Version=6.20
Short Identifier=Floodplain
Geom File=g01
Flow File=f01
Subcritical Flow
K Sum by GR= 0
Std Step Tol= 0.01
Critical Tol= 0.01
Num of Std Step Trials= 20
Max Error Tol= 0.3
Flow Tol Ratio= 0.001
Split Flow NTrial= 30
Split Flow Tol= 0.02
Split Flow Ratio= 0.02
Log Output Level= 0
Friction Slope Method= 1
Unsteady Friction Slope Method= 2
Unsteady Bridges Friction Slope Method= 1
Parabolic Critical Depth
Global Vel Dist= 0 , 0 , 0
Global Log Level= 0
CheckData=True
Encroach Param=-1 ,0,0, 0
Mapping Interval=1HOUR
Computation Time Step Use Courant=        0
Computation Time Step Use Time Series=    0
Computation Time Step Count To Double=0
Computation Time Step Max Doubling=0
Computation Time Step Max Halving=0
Computation Time Step Residence Courant=0
Run HTab= 0
Run UNet= 0
Run Sediment= 0
Run PostProcess= 0
Run WQNet= 0
Run RASMapper=-1
UNET Theta= 0
UNET Theta Warmup= 0
UNET ZTol= 0
UNET ZSATol= 0
UNET MxIter= 0
UNET Max Iter WO Improvement= 0
UNET MaxInSteps= 0
UNET DtIC= 0
UNET DtMin= 0
UNET MaxCRTS= 0
UNET WFStab= 0
UNET SFStab= 0
UNET WFX= 1
UNET SFX= 1
UNET Gravity=32.174
UNET 1D Methodology=Finite Difference
UNET DSS MLevel= 1
UNET Pardiso=0
UNET DZMax Abort= 0
UNET Use Existing IB Tables= 0
UNET Froude Reduction=False
UNET Froude Limit= 0
UNET Froude Power= 0
UNET D1 Cores= 0
UNET WindReference=Eulerian
UNET WindDragFormulation=Hsu (1988)
UNET D2 Coriolis=0
UNET D2 Cores= 0
UNET D2 Theta= 1
UNET D2 Theta Warmup= 1
UNET D2 Z Tol= 0.01
UNET D2 Volume Tol= 0.01
UNET D2 Max Iterations= 20
UNET D2 Equation= 0
UNET D2 RampUpFraction=0.1
UNET D2 TimeSlices= 1
UNET D2 Turbulence Formulation=Non-Conservative (original)
UNET D2 Eddy Viscosity=0.3
UNET D2 Transverse Eddy Viscosity=0.1
UNET D2 Smagorinsky Mixing=0
UNET D2 BCVolumeCheck=0
UNET D2 Cores=0
UNET D2 SolverType=PARDISO (Direct)
UNET D2 Minimum Iterations= 2147483647
UNET D2 Maximum Iterations= 2147483647
UNET D2 Restart Number= 10
UNET D2 Relaxation Coeff=1.3
UNET D2 SOR Precondition Iterations= 10
UNET D2 ILUT Maximum Fill= 8
UNET D2 ILUT Tolerance=1E-08
UNET D1D2 MaxIter= 0
UNET D1D2 ZTol=0.01
UNET D1D2 QTol=0.1
UNET D1D2 MinQTol=1
Write IC File= 0
Write IC File at Fixed DateTime=0
Write IC File at Sim End=0
Echo Input=False
Echo Parameters=False
Echo Output=False
Write Detailed= 0
HDF Write Warmup=0
HDF Write Time Slices=0
HDF Flush=0
HDF Compression= 1
HDF Chunk Size= 1
HDF Spatial Parts= 1
HDF Use Max Rows=0
HDF Fixed Rows= 1
Calibration Method= 0
Calibration Iterations= 20
Calibration Max Change=0.05
Calibration Tolerance=0.2
Calibration Maximum=1.5
Calibration Minimum=0.5
Calibration Optimization Method= 1
WQ AD Non Conservative
WQ ULTIMATE=-1
WQ Max Comp Step=1HOUR
WQ Output Interval=15MIN
WQ Output Selected Increments= 0
WQ Output face flow=0
WQ Output face velocity=0
WQ Output face area=0
WQ Output face dispersion=0
WQ Output cell volume=0
WQ Output cell surface area=0
WQ Output cell continuity=0
WQ Output cumulative cell continuity=0
WQ Output face conc=0
WQ Output face dconc_dx=0
WQ Output face courant=0
WQ Output face peclet=0
WQ Output face adv mass=0
WQ Output face disp mass=0
WQ Output cell mass=0
WQ Output cell source sink temp=0
WQ Output nsm pathways=0
WQ Output nsm derived pathways=0
WQ Create Restart=0
WQ Fixed Restart=0
WQ System Summary=0
WQ Write To DSS=0
Sorting and Armoring Iterations= 10
XS Update Threshold= 0.02
Bed Roughness Predictor= 0
Hydraulics Update Threshold= 0.02
Energy Slope Method= 1
Volume Change Method= 1
Sediment Retention Method= 0
Sediment TS Multiplier= 1
Warm Up Method= 0
XS Weighting Method= 0
Number of US Weighted Cross Sections= 1
Number of DS Weighted Cross Sections= 1
Upstream XS Weight=0
Main XS Weight=1
Downstream XS Weight=0
Number of DS XS's Weighted with US Boundary= 1
Upstream Boundary Weight= 1
Weight of XSs Associated with US Boundary= 0
Number of US XS's Weighted with DS Boundary= 1
Downstream Boundary Weight= 0.5
Weight of XSs Associated with DS Boundary= 0.5
Percentile Method= 0
Sediment Output Level= 3
Mass or Volume Output= 0
Output Increment Type= 1
Profile and TS Output Increment= 1
Transport Output Increment 1
XS Output Flag= 0
XS Output Increment= 10
Read HDF5 Sediment Hotstart= 0
Sediment Hotstart Type= 0
Write Gradation File= 0
Read Gradation Hotstart= 0
Write HDF5 File= 1
Write Binary Output= 1
Write DSS Sediment File= 0
DSS Sediment Output Type= 1
SV Curve= 0
Specific Gage Flag= 0
Subcell Erosion Methods= 0
Subcell Deposition Methods= 0
Advection Scheme= 1
Matrix Solver= 0
Implicit Weighting Factor= 1
Maximum Outer Loop Convergence Iterations= 5
Convergence Maximum Absolute= 0.001
Convergence RMSE= 0.0001
Grain Fractions Max Abs Error= 0.001
Max Subgrid Regions= 1
Max Subgrid Length Scale= 3.402823E+38
Initial Layer Thickness= 3.402823E+38
Min Layer Thickness= 3.402823E+38
Max Layer Thickness= 3.402823E+38
Number of Layers= 5

--- YELLOWCK.f01 (steady flow) ---

Flow Title=Flow
Program Version=6.20
Number of Profiles= 1
Profile Names=P100yr
River Rch & RM=YELLOWCK,Main,6069
     387
River Rch & RM=YELLOWCK,Main,2820
     442
Boundary for River Rch & Prof#=YELLOWCK,Main            , 1
Up Type= 0
Dn Type= 3
Dn Slope=0.00782
DSS Import GetInterval= 0
DSS Import GetPeak= 0
DSS Import FillOption= 0

--- YELLOWCK.g01 (geometry) ---

Geom Title=Geometry
Program Version=6.20

River Reach=YELLOWCK        ,Main
Reach XY= 30
2345274.33455044717375.7568535882345478.95299999717193.039000019
     2345546.315717241.3030000182345581.38400002717215.609000012
2345705.69000001717007.9700000142345706.73100001716891.650000006
2345881.33500002716753.131000012      2345920.28716511.937999994
     2346190.948716441.987000018     2346530.027716266.090000018
2346675.82900001716073.8794972962346838.77618234  716066.2875992
2346948.28100003715938.2080000192347029.77099998715942.106999993
2347195.98473627715840.0187232882347349.34289564715697.784139574
2347403.95299998715535.4000000362347576.34900004715477.153999999
2347631.47100003715374.289000005     2347889.366715327.371000007
2347932.01300003715061.1529999972348145.61600001714825.981999993
2348118.71454462714735.4279441522348009.59200001714666.694000021
2348024.86900003714595.1659999942348394.07500002714428.738000005
2348580.76200002714049.0740000012348762.56500003713930.604000032
2348755.78200001713849.886999995     2348896.308      713878.056

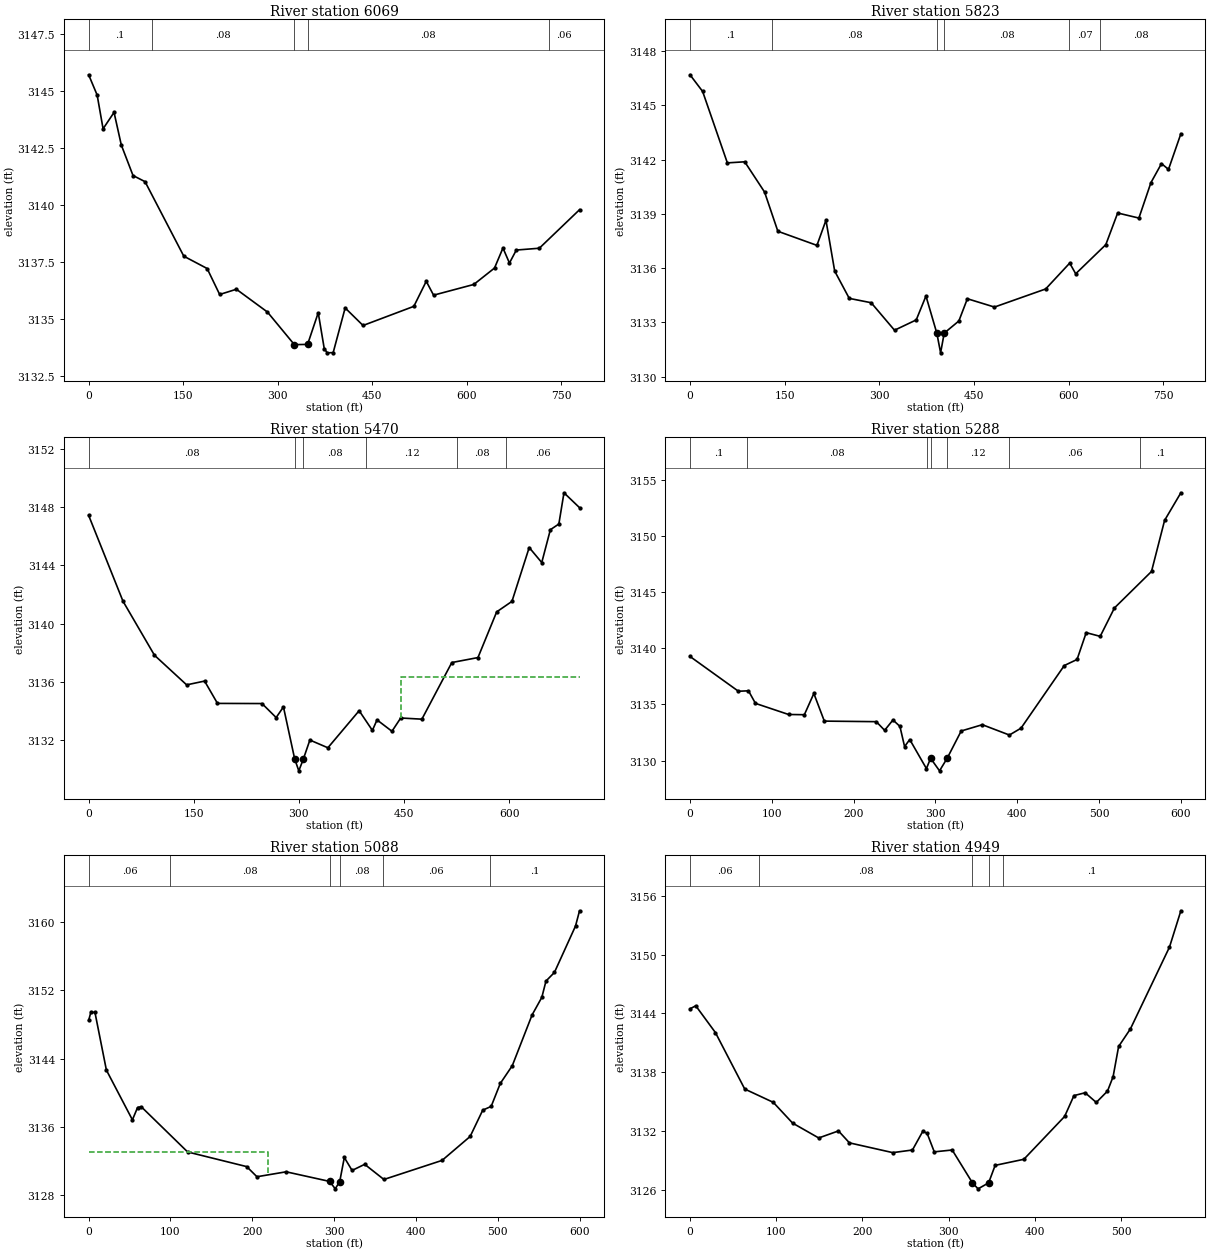
Type RM Length L Ch R = 1 ,6069    ,246,246.4,245.1
XS GIS Cut Line= 2
2345472.33303139717652.5871591222345054.33889146716995.319595795
#Sta/Elev= 30
       0 3145.72    13.5 3144.83    22.9 3143.35    40.3 3144.07    51.8 3142.64
    70.4  3141.3    89.5 3141.03     151 3137.76     188 3137.22   207.9 3136.08
   234.4 3136.31   283.7 3135.31   326.4 3133.88   347.4 3133.89   364.3 3135.28
   373.8 3133.71   378.5 3133.52     388 3133.53     407 3135.49   435.4 3134.72
     516 3135.56   535.7 3136.66   547.3 3136.05   611.1 3136.52     644 3137.24
   657.4 3138.12   667.7 3137.46   678.6 3138.03   715.1 3138.11   778.9  3139.8
#Mann= 5, -1 ,  0
       0     0.1       0     100    0.08       0   326.4   0.045       0
   347.4    0.08       0     730    0.06       0
Bank Sta=326.4,347.4
XS Rating Curve= 0 ,0
Exp/Cntr(USF)=0,0
Exp/Cntr=0.3,0.1

Type RM Length L Ch R = 1 ,5823    ,351.4,353.2,351.5
XS GIS Cut Line= 2
2345676.37316413717537.9670976372345253.54462453 716885.41614674
#Sta/Elev= 30
       0 3146.69      20 3145.77    59.2 3141.82    86.7 3141.88   118.1 3140.21
   139.2 3138.04   201.1 3137.26   215.4 3138.65   229.2 3135.84   252.3 3134.33
     287 3134.09     324 3132.57   358.4 3133.14   373.8 3134.46  391.05  3132.4
     397 3131.32   402.7 3132.41   425.9 3133.08   439.4 3134.31   482.3 3133.85
   563.4 3134.85   601.5 3136.28     611 3135.69   658.7  3137.3   677.5 3139.05
   711.1 3138.77   730.2 3140.73   746.9 3141.78     758 3141.46   777.6 3143.43
#Mann= 6, -1 ,  0
       0     0.1       0     130    0.08       0  391.05   0.045       0
   402.7    0.08       0     600    0.07       0     650    0.08       0
Bank Sta=391.05,402.7
XS Rating Curve= 0 ,0
Exp/Cntr(USF)=0,0
Exp/Cntr=0.3,0.1

Type RM Length L Ch R = 1 ,5470    ,181.3,182.1,179.1
XS GIS Cut Line= 4
2345889.51405265717251.7268953712345676.27907216717081.738504052
2345623.26187406716981.6912028122345387.54347058716773.642366032
#Sta/Elev= 30
       0 3147.42      49 3141.54    93.9 3137.84   139.8 3135.81   165.4 3136.07
   183.8 3134.54   247.3 3134.53   267.5 3133.57   277.9  3134.3   293.9 3130.74
   299.8 3129.92  306.18 3130.71   315.6 3132.03   341.3  3131.5   385.9 3134.04
   404.8 3132.69   411.4 3133.41   432.7 3132.63   445.2 3133.54   475.4 3133.46
   518.1 3137.34   555.4 3137.68   582.1 3140.81   603.9 3141.53   628.5 3145.22
   646.4 3144.19   658.7 3146.44   670.8 3146.83   678.1 3148.97   700.3 3147.95
#Mann= 6, -1 ,  0
       0    0.08       0   293.9   0.045       0  306.18    0.08       0
  395.93    0.12       0  525.93    0.08       0  595.93    0.06       0
#XS Ineff= 2 , 0
                             445         3136.37
Permanent Ineff=
       F       F
Bank Sta=293.9,306.18
XS Rating Curve= 0 ,0
Exp/Cntr(USF)=0,0
Exp/Cntr=0.3,0.1

Type RM Length L Ch R = 1 ,5288    ,199.5,200,201.3
XS GIS Cut Line= 2
2345938.53497997717083.2854121662345468.58034033716710.267132887
#Sta/Elev= 30
       0 3139.28    59.2 3136.18    71.5 3136.22      80  3135.1   120.5 3134.11
   139.8 3134.09   151.4 3135.98   164.2 3133.52   227.7 3133.47   237.9  3132.7
   248.1 3133.62   256.6 3133.05   262.3 3131.25   268.6 3131.88     289 3129.29
   294.1 3130.21     305 3129.09   314.5 3130.23   331.5 3132.64   357.3  3133.2
   390.4 3132.28   404.6 3132.89   457.5 3138.47   473.1 3139.01   484.3  3141.4
   501.4 3141.07   518.8  3143.6   564.1 3146.85   580.1  3151.4     600 3153.86
#Mann= 7, -1 ,  0
       0     0.1       0      70    0.08       0     290    0.12       0
   294.1   0.045       0   314.5    0.12       0     390    0.06       0
     550     0.1       0
Bank Sta=294.1,314.5
XS Rating Curve= 0 ,0
Exp/Cntr(USF)=0,0
Exp/Cntr=0.3,0.1

Type RM Length L Ch R = 1 ,5088    ,140.9,138.7,135.4
XS GIS Cut Line= 2
 2346090.1166203716966.8780484232345624.36075276716588.630151061
#Sta/Elev= 30
       0 3148.48     2.7 3149.43     7.7 3149.42    21.7 3142.64    53.5  3136.8
    59.8 3138.25    64.3 3138.34     121 3133.03   193.2 3131.31   205.7 3130.12
   241.4  3130.7   294.6 3129.57   301.4  3128.7   306.9 3129.56   312.5 3132.38
     322 3130.86   337.4 3131.58   360.9  3129.8     432 3132.04   466.3 3134.85
   481.7 3137.94     492 3138.38   503.1 3141.07   517.8 3143.16     542 3149.12
   553.9 3151.18     559  3153.1   569.3 3154.11   595.1 3159.56     600 3161.35
#Mann= 6, -1 ,  0
       0    0.06       0     100    0.08       0   294.6   0.045       0
   306.9    0.08       0     360    0.06       0     490     0.1       0
#XS Ineff= 2 , 0
          218.78 3132.99
Permanent Ineff=
       F       F
Bank Sta=294.6,306.9
XS Rating Curve= 0 ,0
Exp/Cntr(USF)=0,0
Exp/Cntr=0.3,0.1

Type RM Length L Ch R = 1 ,4949    ,269.3,278.5,285.9
XS GIS Cut Line= 4
2346165.23343612716861.5811812892345969.90204969716670.595579137
2345823.31530987716629.4365748922345710.13598783716540.631933705
#Sta/Elev= 30
       0 3144.47     6.7 3144.78    29.5 3142.04    63.5 3136.27    96.6 3134.91
     119 3132.79   149.3 3131.27   172.2 3131.99   184.9 3130.77   235.2 3129.77
     258 3130.04     270 3131.95     275 3131.75   283.3 3129.85   304.1 3130.04
   327.6 3126.68   334.1 3126.07  346.33 3126.68   353.9 3128.47   387.2 3129.09
   434.5 3133.47   445.3  3135.6   458.3 3135.89   471.2  3134.9   484.2 3136.06
   490.7 3137.53   497.1 3140.62   510.8 3142.42   556.1 3150.78   569.3 3154.49
#Mann= 5, -1 ,  0
       0    0.06       0      80    0.08       0   327.6   0.045       0
  346.33    0.06       0  363.18     0.1       0
Bank Sta=327.6,346.33
XS Rating Curve= 0 ,0
Exp/Cntr(USF)=0,0
Exp/Cntr=0.3,0.1

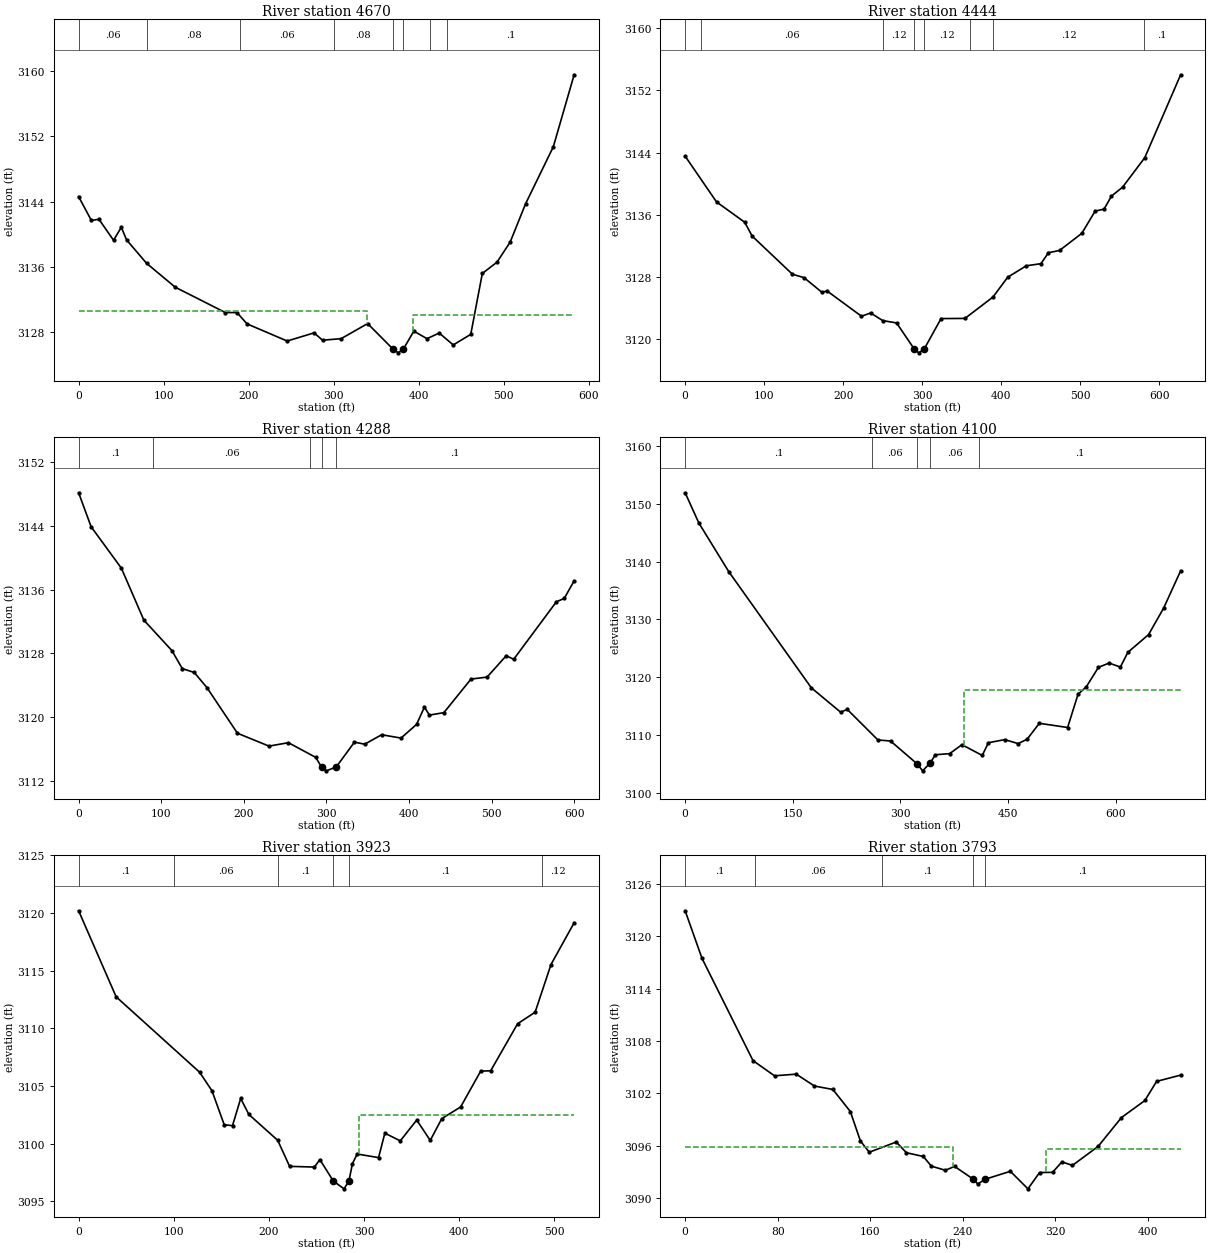
Type RM Length L Ch R = 1 ,4670    ,228.2,226,223.3
XS GIS Cut Line= 4
2346208.28169411716809.4017548772346049.84403741716513.585897132
2346041.20722694716456.8297140132345893.77933957716337.086071872
#Sta/Elev= 30
       0 3144.61      15 3141.68    23.9 3141.83    41.1 3139.25    50.2 3140.85
    56.4  3139.3      80 3136.42   113.7 3133.49   172.7 3130.38   186.3 3130.38
   198.2 3128.99   245.3 3126.89     277 3127.89   286.9 3126.99   308.8 3127.18
     340 3129.03   369.73125.912     376 3125.44  382.08 3125.91   394.3  3128.1
   409.8 3127.18   424.2 3127.87   440.7 3126.41   461.3 3127.71   474.9 3135.18
   492.2 3136.57   507.7 3139.04   525.7 3143.71   558.4 3150.72   582.9 3159.56
#Mann= 8, -1 ,  0
       0    0.06       0      80    0.08       0     190    0.06       0
     300    0.08       0   369.7   0.045       0  382.08    0.08       0
  412.98    0.12       0  432.98     0.1       0
#XS Ineff= 2 , 0
          338.84 3130.63  393.78         3130.14
Permanent Ineff=
       F       F
Bank Sta=369.7,382.08
XS Rating Curve= 0 ,0
Exp/Cntr(USF)=0,0
Exp/Cntr=0.3,0.1

Type RM Length L Ch R = 1 ,4444    ,156.8,156.8,156.7
XS GIS Cut Line= 2
2346410.44249583716657.5399988882346083.78176907 716122.42306444
#Sta/Elev= 30
       0 3143.54    39.7 3137.66    75.4 3135.05    84.8 3133.27   135.8 3128.37
   150.4 3127.94   173.2 3126.04   179.4 3126.24   223.1 3122.98   234.7  3123.4
     250 3122.42   267.5 3122.12     290 3118.75   295.7 3118.28  302.38 3118.76
   323.8 3122.68     354  3122.7   389.4 3125.44   408.1 3127.99   431.6 3129.46
   450.1 3129.73   459.7 3131.14   473.7 3131.43   501.9 3133.63   518.7 3136.48
     530 3136.74   539.4 3138.41   553.4 3139.55   581.5 3143.34   626.9 3153.99
#Mann= 8, -1 ,  0
       0     0.1       0      20    0.06       0     250    0.12       0
     290   0.045       0  302.38    0.12       0     360     0.1       0
     390    0.12       0     580     0.1       0
Bank Sta=290,302.38
XS Rating Curve= 0 ,0
Exp/Cntr(USF)=0,0
Exp/Cntr=0.3,0.1

Type RM Length L Ch R = 1 ,4288    ,187.8,188,185.1
XS GIS Cut Line= 2
2346548.89224633716581.2266841622346233.26167157716070.954854372
#Sta/Elev= 30
       0 3148.19    15.1 3143.92    51.8  3138.7      79 3132.17   112.9 3128.35
   125.5 3126.08     140 3125.59   155.3  3123.7   192.3 3117.95   230.5 3116.33
     254 3116.76     287 3114.92   294.1 3113.71   299.9 3113.22  311.96 3113.71
     334 3116.83   346.4 3116.57   366.9 3117.76   390.4 3117.34   409.2 3119.06
   418.7 3121.23   424.8 3120.23   442.3 3120.54   475.1 3124.76   494.6 3125.01
   517.8  3127.7   526.8 3127.25   578.6 3134.49     588  3134.9     600 3137.11
#Mann= 5, -1 ,  0
       0     0.1       0      90    0.06       0     280     0.1       0
   294.1   0.045       0  311.96     0.1       0
Bank Sta=294.1,311.96
XS Rating Curve= 0 ,0
Exp/Cntr(USF)=0,0
Exp/Cntr=0.3,0.1

Type RM Length L Ch R = 1 ,4100    ,174.8,176.5,172.6
XS GIS Cut Line= 2
2346764.44698658716491.8737657672346323.60453736715960.542603291
#Sta/Elev= 30
       0 3151.96    19.2  3146.7    60.7 3138.31   175.8 3118.16   216.6 3113.94
   225.9 3114.42   268.6 3109.12   286.2 3108.94   323.1 3104.99   330.9 3103.77
   341.3 3105.12   348.7 3106.56   368.6 3106.75   385.6  3108.3     414 3106.44
   422.5 3108.64   445.3 3109.18     464 3108.49   476.5 3109.25   493.5 3112.01
   532.9 3111.28   547.5 3117.06   558.9 3118.32   575.9 3121.71   590.8 3122.45
   606.4 3121.75   616.8  3124.3   645.7 3127.38   666.8 3131.99   690.4 3138.44
#Mann= 5, -1 ,  0
       0     0.1       0     260    0.06       0   323.1   0.045       0
   341.3    0.06       0     410     0.1       0
#XS Ineff= 2 , 0
                          388.58         3117.71
Permanent Ineff=
       F       F
Bank Sta=323.1,341.3
XS Rating Curve= 0 ,0
Exp/Cntr(USF)=0,0
Exp/Cntr=0.3,0.1

Type RM Length L Ch R = 1 ,3923    ,118.1,129.5,130.4
XS GIS Cut Line= 4
2346770.97988788716343.0285012092346684.54334425716129.648462506
 2346616.3501861716060.6461430062346469.76587953715934.430559852
#Sta/Elev= 30
       0  3120.2    39.4 3112.74   127.2 3106.19   140.1 3104.59     153 3101.64
   161.7 3101.56   170.3 3103.92   178.9 3102.53   209.2 3100.29   221.7 3098.03
   247.8 3097.97   253.5 3098.62   267.6 3096.76   278.9 3096.08  284.05 3096.75
   287.7 3098.26   292.7  3099.1   315.2 3098.79   321.8 3100.91     338 3100.24
   355.3 3102.05   369.5 3100.28   381.6 3102.17   401.4 3103.18   422.5 3106.29
     433 3106.32   461.3  3110.4   479.7  3111.4   496.4 3115.54   520.7 3119.16
#Mann= 6, -1 ,  0
       0     0.1       0     100    0.06       0     210     0.1       0
   267.6   0.045       0  284.05     0.1       0  487.24    0.12       0
#XS Ineff= 2 , 0
                           294.4          3102.5
Permanent Ineff=
       F       F
Bank Sta=267.6,284.05
XS Rating Curve= 0 ,0
Exp/Cntr(USF)=0,0
Exp/Cntr=0.3,0.1

Type RM Length L Ch R = 1 ,3793    ,179.1,180.4,168.4
XS GIS Cut Line= 4
2346841.12593261716306.3530808432346752.60522288716118.483155971
2346747.10353336716064.0404795232346615.71934817715962.297500008
#Sta/Elev= 30
       0 3122.94    14.6 3117.48    58.7 3105.76    77.3 3104.02    96.1 3104.21
   111.8 3102.85   127.8 3102.45   142.9 3099.92   151.6 3096.55   159.3 3095.26
   182.6 3096.43   191.4  3095.2     206 3094.77     213 3093.66   225.1 3093.19
   233.1 3093.63   249.4 3092.15   253.2 3091.61  259.25 3092.15   281.3 3093.07
   296.5 3091.06   306.6 3092.93   317.8 3092.95   325.9 3094.15     335 3093.75
   357.2 3095.92   377.4 3099.23   397.7 3101.19   407.8 3103.38   428.6  3104.1
#Mann= 5, -1 ,  0
       0     0.1       0      60    0.06       0     170     0.1       0
   249.4   0.045       0  259.25     0.1       0
#XS Ineff= 2 , 0
          231.77 3095.85  311.76         3095.67
Permanent Ineff=
       F       F
Bank Sta=249.4,259.25
XS Rating Curve= 0 ,0
Exp/Cntr(USF)=0,0
Exp/Cntr=0.3,0.1

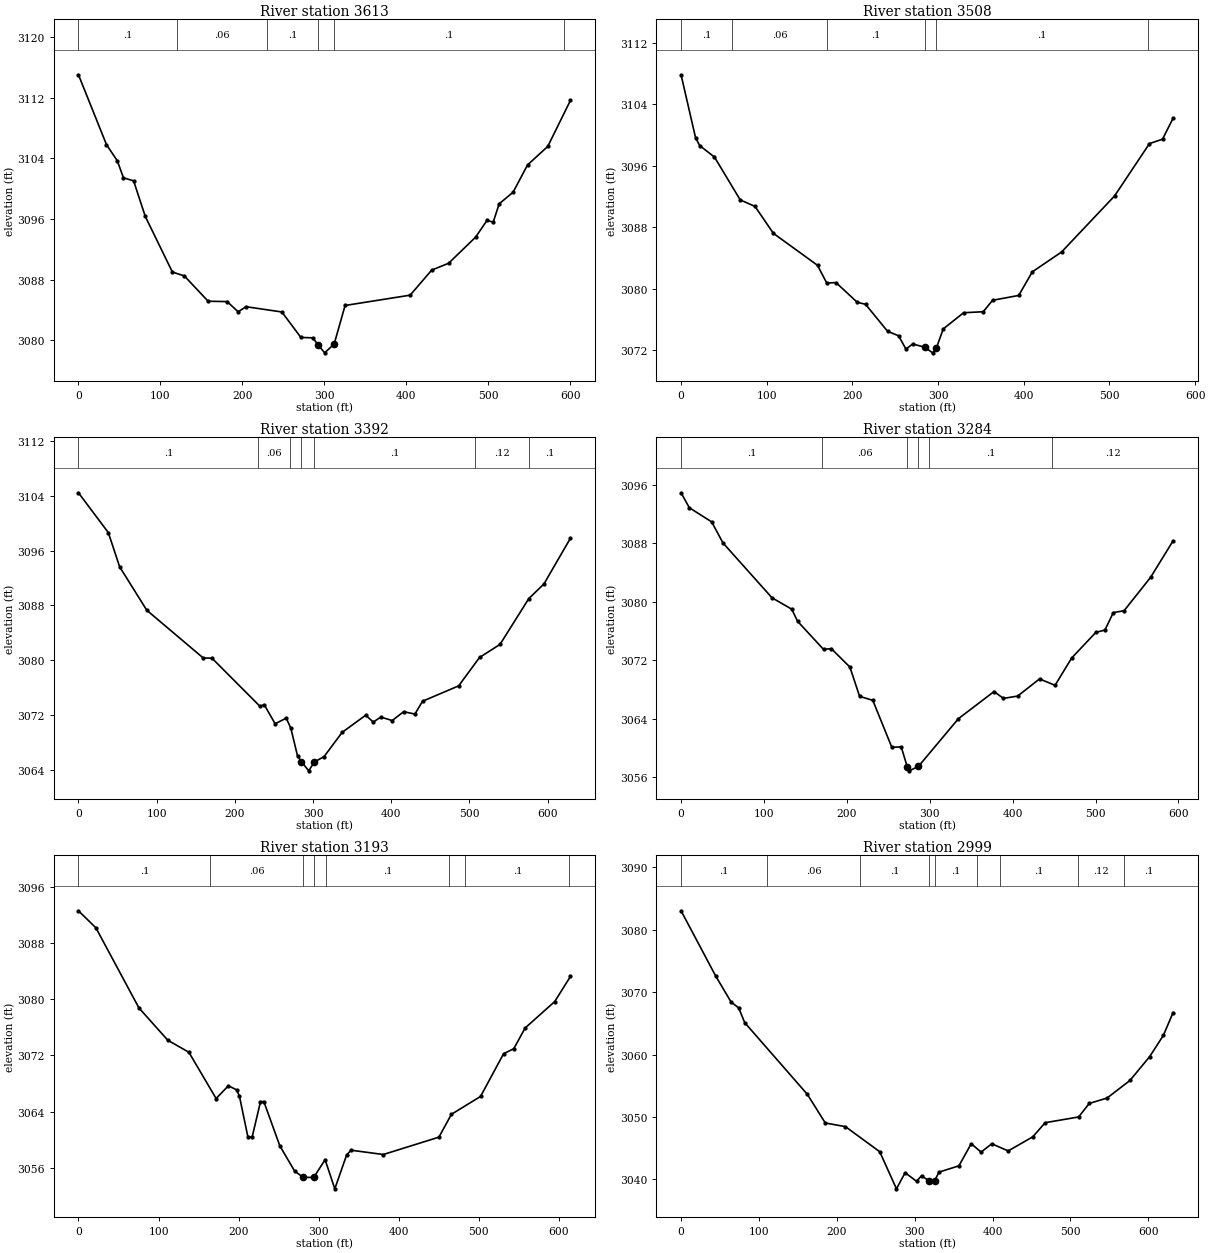
Type RM Length L Ch R = 1 ,3613    ,103.8,104.6,104.4
XS GIS Cut Line= 3
2347025.41719427716250.1409867332346832.15406524715943.008157748
2346692.85974445715750.735797963
#Sta/Elev= 30
       0 3115.02    34.2  3105.8    47.4 3103.67    54.9 3101.43    67.3 3101.02
    81.5 3096.34   114.6 3088.99   129.2 3088.48   158.2 3085.14   181.4 3085.09
   194.9 3083.74   204.4 3084.42   248.2 3083.72   271.4 3080.36   285.9 3080.31
   292.3 3079.39   300.4 3078.33     312  3079.5   325.3 3084.58   404.7 3085.94
     431 3089.25   451.5 3090.14   484.5 3093.59   498.5 3095.81     506 3095.57
   513.3 3097.99   530.3 3099.53   547.9 3103.12   572.6 3105.57   600.3 3111.65
#Mann= 6, -1 ,  0
       0     0.1       0     120    0.06       0     230     0.1       0
   292.3   0.045       0     312     0.1       0  592.88    0.12       0
Bank Sta=292.3,312
XS Rating Curve= 0 ,0
Exp/Cntr(USF)=0,0
Exp/Cntr=0.3,0.1

Type RM Length L Ch R = 1 ,3508    ,117.4,116.1,114.4
XS GIS Cut Line= 4
 2347054.3731535716209.5130636682346953.89387779715953.946210233
2346921.12889658715892.0568012812346779.14731134715711.485349281
#Sta/Elev= 30
       0 3107.86    16.9 3099.68    21.8 3098.64      39 3097.15    69.1 3091.57
    86.3 3090.73   107.8 3087.22   159.3 3083.06     170 3080.76   180.9 3080.81
   205.6 3078.25   215.3 3077.99     241 3074.48   253.9 3073.89   262.5 3072.16
   270.4 3072.82   284.5  3072.4   293.6 3071.67   298.1 3072.32     306 3074.78
   329.8 3076.89   352.7 3077.02   363.6 3078.51   394.1 3079.14     410 3082.21
   444.2  3084.8     506 3092.09   546.7  3098.9     562 3099.48   574.3 3102.21
#Mann= 6, -1 ,  0
       0     0.1       0      60    0.06       0     170     0.1       0
   284.5   0.045       0   298.1     0.1       0  544.64    0.12       0
Bank Sta=284.5,298.1
XS Rating Curve= 0 ,0
Exp/Cntr(USF)=0,0
Exp/Cntr=0.3,0.1

Type RM Length L Ch R = 1 ,3392    ,108.8,108.1,104
XS GIS Cut Line= 3
2347222.02847834716172.7236293332346942.29365524715762.307802998
2346859.69718495715658.707420781
#Sta/Elev= 30
       0 3104.46    38.2 3098.64    52.7 3093.63    87.4 3087.29   159.5 3080.32
   170.8 3080.28   231.8 3073.29   237.7 3073.46   251.5  3070.7   265.7 3071.52
   271.6 3070.05   280.2 3065.97   285.1 3065.15   294.5 3063.82   301.6 3065.11
   314.1  3065.9   337.1 3069.43   367.3 3071.95     377 3070.95   386.7 3071.68
   401.2 3071.17   415.8 3072.46   430.3 3072.12     440 3073.99   486.2 3076.24
   512.9 3080.39   539.1  3082.3   575.8 3088.98   595.3 3091.14   629.2 3097.83
#Mann= 7, -1 ,  0
       0     0.1       0     230    0.06       0     270     0.1       0
   285.1   0.045       0   301.6     0.1       0  506.68    0.12       0
  576.68     0.1       0
Bank Sta=285.1,301.6
XS Rating Curve= 0 ,0
Exp/Cntr(USF)=0,0
Exp/Cntr=0.3,0.1

Type RM Length L Ch R = 1 ,3284    ,94.7,96.3,97.8
XS GIS Cut Line= 4
2347287.19173888716102.0696785582347182.03580818715898.894030077
2347061.30995842715811.9030049662346930.97086317715639.690263728
#Sta/Elev= 30
       0 3094.94      10 3092.89      37 3090.95    50.5 3088.08   109.7 3080.56
   133.5    3079   140.6 3077.34   171.9 3073.49   181.2  3073.6   203.7 3071.07
   215.4 3067.06   231.3 3066.52   254.3 3060.08   265.6 3060.15   272.8 3057.44
   275.4 3056.86   286.4 3057.47   334.6    3064   377.6 3067.72   388.9 3066.78
   406.1  3067.1   432.5 3069.45   451.2 3068.57   471.3 3072.32   500.3 3075.81
   511.4 3076.15   521.5 3078.53   534.5 3078.79   566.6 3083.38   593.6 3088.36
#Mann= 6, -1 ,  0
       0     0.1       0     170    0.06       0   272.8   0.045       0
   286.4    0.06       0  298.78     0.1       0  447.58    0.12       0
Bank Sta=272.8,286.4
XS Rating Curve= 0 ,0
Exp/Cntr(USF)=0,0
Exp/Cntr=0.3,0.1

Type RM Length L Ch R = 1 ,3193    ,193.8,194.6,193.6
XS GIS Cut Line= 5
2347398.02324584716022.1262806982347325.79684661 715946.38717194
 2347225.6802751715829.338148361 2347161.8799225715759.848888109
2346994.83237777715558.846339374
#Sta/Elev= 30
       0 3092.61    21.8 3090.18    75.5 3078.78   111.5 3074.18   137.9 3072.46
   171.9 3065.87   187.2 3067.69   197.4 3067.11     201 3066.21   211.5 3060.45
   216.8 3060.35   227.3 3065.41   231.5 3065.44   251.4 3059.15   269.8 3055.56
   280.6 3054.64   293.8 3054.64     308 3057.16   320.1 3053.01   334.9 3057.84
   340.4 3058.51   380.7  3057.9   450.1 3060.37   465.7 3063.62   502.1 3066.17
   530.9 3072.26   543.6 3072.97   557.8 3075.92   594.7 3079.68   614.4 3083.26
#Mann= 8, -1 ,  0
       0     0.1       0  164.66    0.06       0   280.6   0.045       0
   293.8    0.06       0  308.68     0.1       0  463.02    0.12       0
  483.02     0.1       0  613.02    0.12       0
Bank Sta=280.6,293.8
XS Rating Curve= 0 ,0
Exp/Cntr(USF)=0,0
Exp/Cntr=0.3,0.1

Type RM Length L Ch R = 1 ,2999    ,177,179.1,183.4
XS GIS Cut Line= 5
2347548.91086589715946.0759668662347400.00089637715729.979468277
2347315.93956609715663.407408055 2347205.9963646715535.466369843
 2347152.4016151715458.961326909
#Sta/Elev= 30
       0 3083.04    44.3 3072.62    64.2 3068.42      74 3067.47    81.7 3065.12
   162.2 3053.61   185.2 3049.03   211.1 3048.44   255.1 3044.42   276.6 3038.47
   287.7 3041.06   302.4 3039.68   308.8 3040.57   318.3 3039.75   325.5 3039.75
   331.2 3041.15   356.8 3042.16   372.6  3045.7   385.3 3044.36     399 3045.69
   420.1 3044.55   451.7 3046.81   467.5 3049.07   510.5 3049.99   524.2 3052.16
     547 3053.02   576.4 3055.84   601.6 3059.64   619.3 3063.06   631.8 3066.72
#Mann= 9, -1 ,  0
       0     0.1       0     110    0.06       0     230     0.1       0
   318.3   0.045       0   325.5     0.1       0  379.66    0.12       0
  409.66     0.1       0  509.66    0.12       0  568.35     0.1       0
Bank Sta=318.3,325.5
XS Rating Curve= 0 ,0
Exp/Cntr(USF)=0,0
Exp/Cntr=0.3,0.1

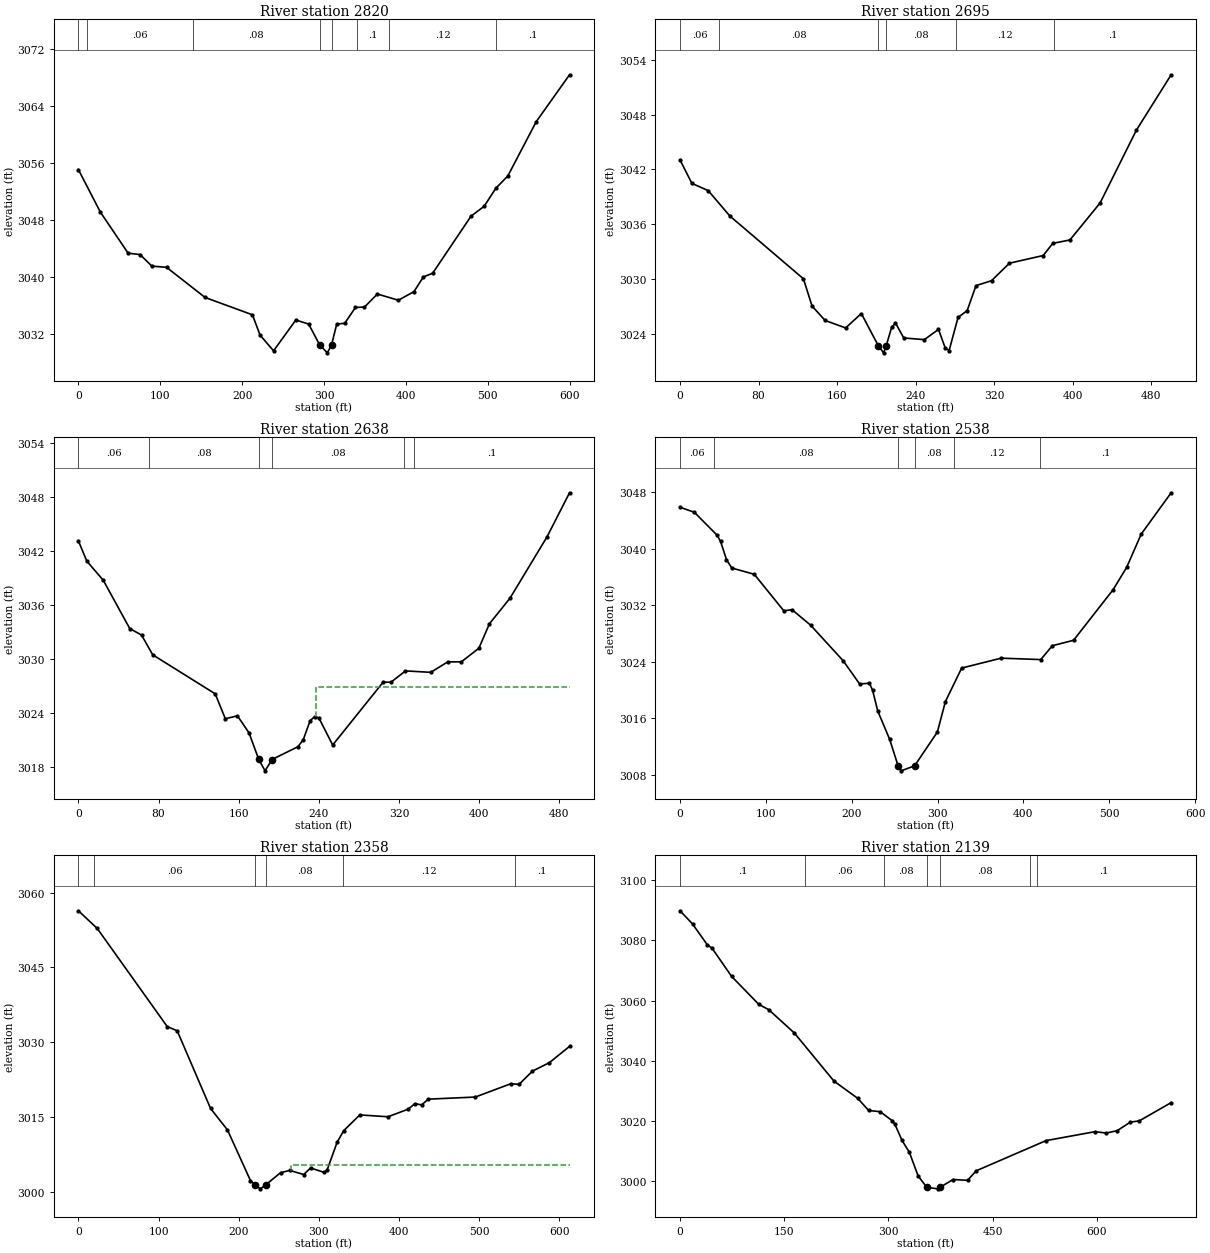
Type RM Length L Ch R = 1 ,2820    ,121.5,124.7,129
XS GIS Cut Line= 2
2347592.30495115715770.5136690362347234.96524327715288.529921208
#Sta/Elev= 30
       0 3055.11    26.8 3049.15    60.7 3043.38    75.4 3043.18    89.7 3041.56
   107.7 3041.39   154.7 3037.16   212.6 3034.72   221.9 3031.88   238.4 3029.66
   265.6 3033.99   281.3 3033.42   294.6 3030.52   304.1 3029.38   309.2 3030.47
   315.6 3033.43   325.3 3033.52   338.5 3035.76   349.5 3035.81   365.2 3037.64
   390.9 3036.77     410 3037.98   421.4 3040.04   432.8 3040.56   479.7 3048.58
   495.7 3049.96     510  3052.5   524.5  3054.2   559.4 3061.86     600 3068.43
#Mann= 8, -1 ,  0
       0     0.1       0      10    0.06       0     140    0.08       0
   294.6   0.045       0   309.2    0.08       0     340     0.1       0
     380    0.12       0     510     0.1       0
Bank Sta=294.6,309.2
XS Rating Curve= 0 ,0
Exp/Cntr(USF)=0,0
Exp/Cntr=0.3,0.1

Type RM Length L Ch R = 1 ,2695    ,62.6,57.7,52.7
XS GIS Cut Line= 4
2347602.22546515715671.1774309252347524.40111698715503.694645004
2347529.29611559715467.5734512972347317.06374839715286.161390458
#Sta/Elev= 30
       0 3043.03    12.1 3040.46    28.7 3039.67    50.7 3036.89   125.7    3030
   134.5 3027.01   147.8 3025.43   168.7 3024.61   184.7 3026.19   201.9 3022.68
   207.4 3021.88  209.983022.633   215.5 3024.66   219.5 3025.15   227.9 3023.51
   248.9 3023.33   263.3 3024.45     270 3022.46   274.1 3022.12   283.2 3025.76
   292.5 3026.51   301.5 3029.25   317.3 3029.79   335.6 3031.71   369.9 3032.55
   379.7 3033.88   397.2 3034.26   427.9 3038.31   464.9  3046.3   500.3 3052.37
#Mann= 6, -1 ,  0
       0    0.06       0      40    0.08       0   201.9   0.045       0
  209.98    0.08       0  281.13    0.12       0  381.13     0.1       0
Bank Sta=201.9,209.98
XS Rating Curve= 0 ,0
Exp/Cntr(USF)=0,0
Exp/Cntr=0.3,0.1

Type RM Length L Ch R = 1 ,2638    ,98.1,99.2,100.4
XS GIS Cut Line= 4
2347694.49873991715620.5222462082347665.21730062715567.496036745
2347549.52260825715436.5783585342347366.84677819715258.469424223
#Sta/Elev= 30
       0 3043.13     8.4 3040.88    24.8 3038.76    51.3 3033.38      63 3032.67
    74.2 3030.47   136.6 3026.13   146.7 3023.36   158.8 3023.69   170.4 3021.78
  180.053018.841   186.4 3017.57   193.3 3018.83   219.2 3020.25   224.5 3021.03
   231.3 3023.12   235.8  3023.6   240.2 3023.43   253.9 3020.44   304.2 3027.42
   312.2 3027.43   326.6 3028.68   351.8 3028.52   368.8 3029.68   382.4 3029.69
   399.9  3031.2   410.4 3033.92     431 3036.77   467.8 3043.56   490.4 3048.48
#Mann= 6, -1 ,  0
       0    0.06       0   70.57    0.08       0  180.05   0.045       0
   193.3    0.08       0  325.29    0.12       0  335.29     0.1       0
#XS Ineff= 2 , 0
                          237.14         3026.92
Permanent Ineff=
       F       F
Bank Sta=180.05,193.3
XS Rating Curve= 0 ,0
Exp/Cntr(USF)=0,0
Exp/Cntr=0.3,0.1

Type RM Length L Ch R = 1 ,2538    ,175.7,180.9,185.8
XS GIS Cut Line= 4
   2347764.09156715600.4700777082347712.40855672715482.247316049
2347474.92997764715221.9342582112347386.06910479715240.070567261
#Sta/Elev= 30
       0  3045.9    16.7 3045.19    42.9 3041.98    47.2 3041.08    54.1 3038.49
    60.3  3037.3    86.5 3036.41   120.9 3031.24   130.5  3031.4   152.1 3029.21
     190 3024.18   209.2 3020.89   220.6 3020.99   224.3 3020.01   230.3 3017.07
   244.2 3013.05     254 3009.31   257.4 3008.59  273.223009.292   299.8 3014.09
   309.1 3018.39   328.1 3023.14   374.1 3024.54   420.2 3024.34   433.7  3026.3
   458.4 3027.07   504.6 3034.25   520.4 3037.42   537.2  3042.1   572.1 3047.95
#Mann= 6, -1 ,  0
       0    0.06       0      40    0.08       0     254   0.045       0
  273.22    0.08       0  319.03    0.12       0  419.03     0.1       0
Bank Sta=254,273.22
XS Rating Curve= 0 ,0
Exp/Cntr(USF)=0,0
Exp/Cntr=0.3,0.1

Type RM Length L Ch R = 1 ,2358    ,225.7,218.2,210.4
XS GIS Cut Line= 3
2347859.04447554715579.8281395462347762.64440999715238.679542633
2347515.98319636715161.845621152
#Sta/Elev= 30
       0 3056.36    23.5 3052.82   110.8 3033.17   123.3 3032.31   164.9 3016.76
     186 3012.46   214.7 3002.31   219.8  3001.5   227.2 3000.65  234.163001.491
   252.2 3003.88   263.7 3004.34   281.2 3003.52   289.7 3004.83   306.8 3003.94
   310.3 3004.39   322.8 3009.96   331.1 3012.31   351.2 3015.46   386.4 3015.09
   411.6 3016.62   419.9 3017.72   428.3 3017.47   436.7 3018.62   495.3 3019.04
   539.8 3021.72   549.8 3021.57   566.6 3024.23   587.7 3025.93   612.9 3029.19
#Mann= 6, -1 ,  0
       0     0.1       0      20    0.06       0   219.8   0.045       0
  234.16    0.08       0     330    0.12       0  544.51     0.1       0
#XS Ineff= 2 , 0
                          264.82         3005.34
Permanent Ineff=
       F       F
Bank Sta=219.8,234.16
XS Rating Curve= 0 ,0
Exp/Cntr(USF)=0,0
Exp/Cntr=0.3,0.1

Type RM Length L Ch R = 1 ,2139    ,120.3,120.7,122.3
XS GIS Cut Line= 3
2348204.97079978 715412.867570272348045.32586555715255.307660212
2347584.16073255715112.272485273
#Sta/Elev= 30
       0 3089.78      18 3085.42    39.4 3078.45    46.1 3077.38    74.2 3068.03
   113.5 3058.72   127.6    3057   164.7 3049.22   221.6 3033.29   255.7 3027.59
   271.6 3023.55   288.3 3023.13   305.1 3020.21   309.3 3019.02   319.6 3013.63
   330.2 3009.67   342.8 3001.83   355.3 2998.06   370.8 2997.55  373.992998.008
     393 3000.63     414 3000.38   426.5 3003.54     527 3013.55   597.7 3016.52
   613.7 3016.04   629.6 3016.87   648.5 3019.69   661.1 3020.08   707.1 3026.15
#Mann= 7, -1 ,  0
       0     0.1       0     180    0.06       0   294.3    0.08       0
   355.3   0.045       0  373.99    0.08       0   504.3    0.12       0
   514.3     0.1       0
Bank Sta=355.3,373.99
XS Rating Curve= 0 ,0
Exp/Cntr(USF)=0,0
Exp/Cntr=0.3,0.1