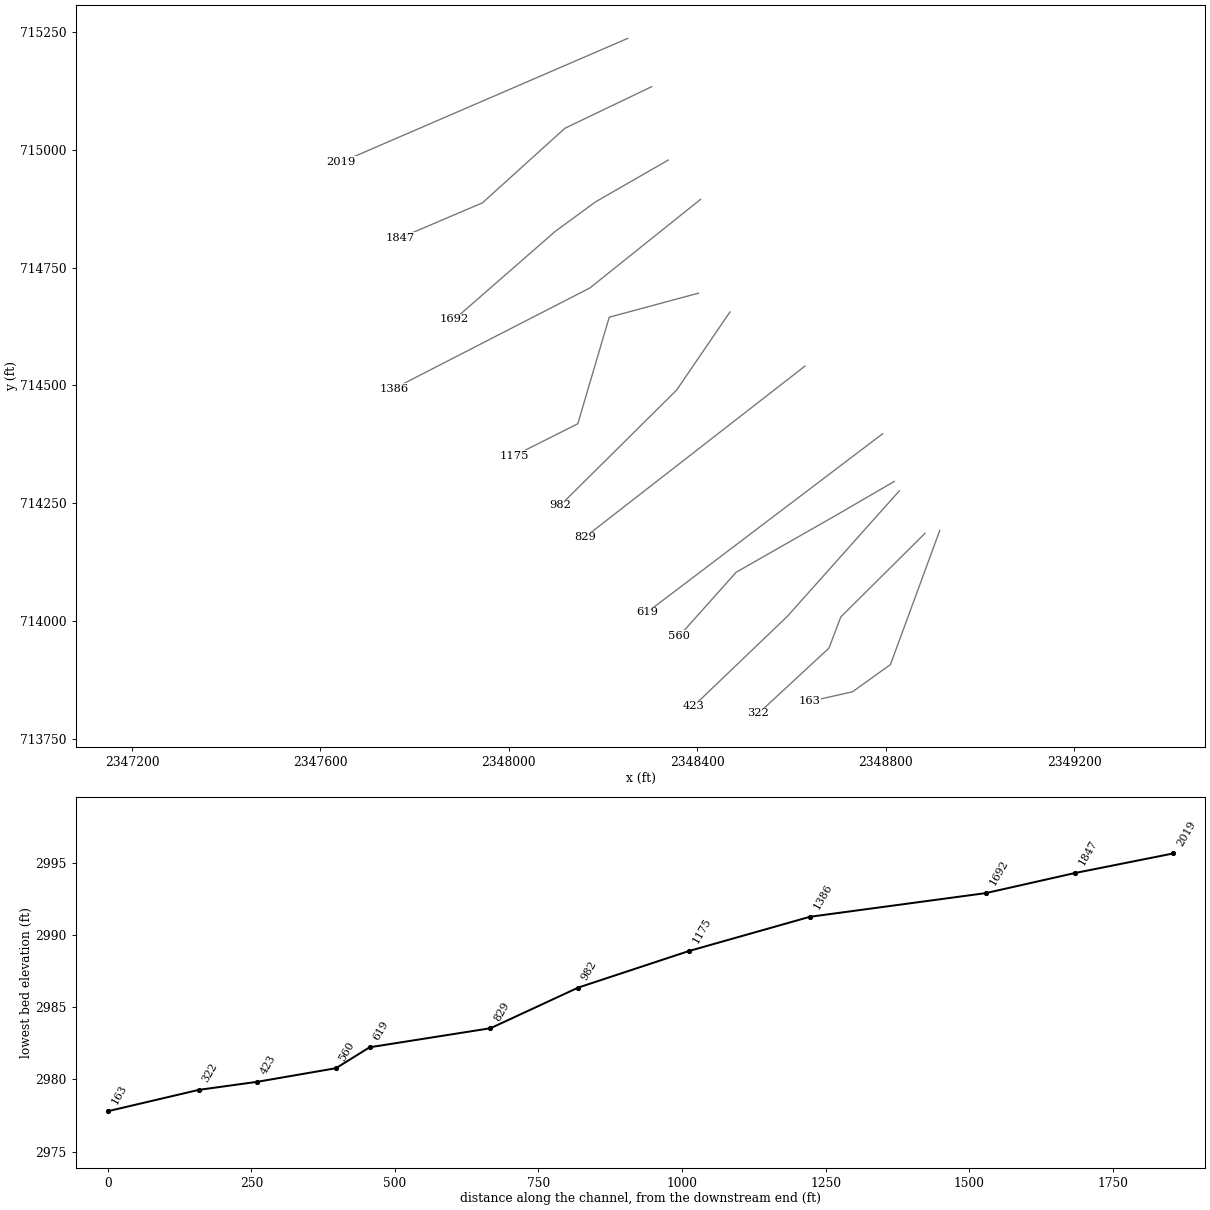
HEC-RAS study YELLOWCK.prj: YELLOWCK

--- YELLOWCK.g01 (geometry) --- (continued)

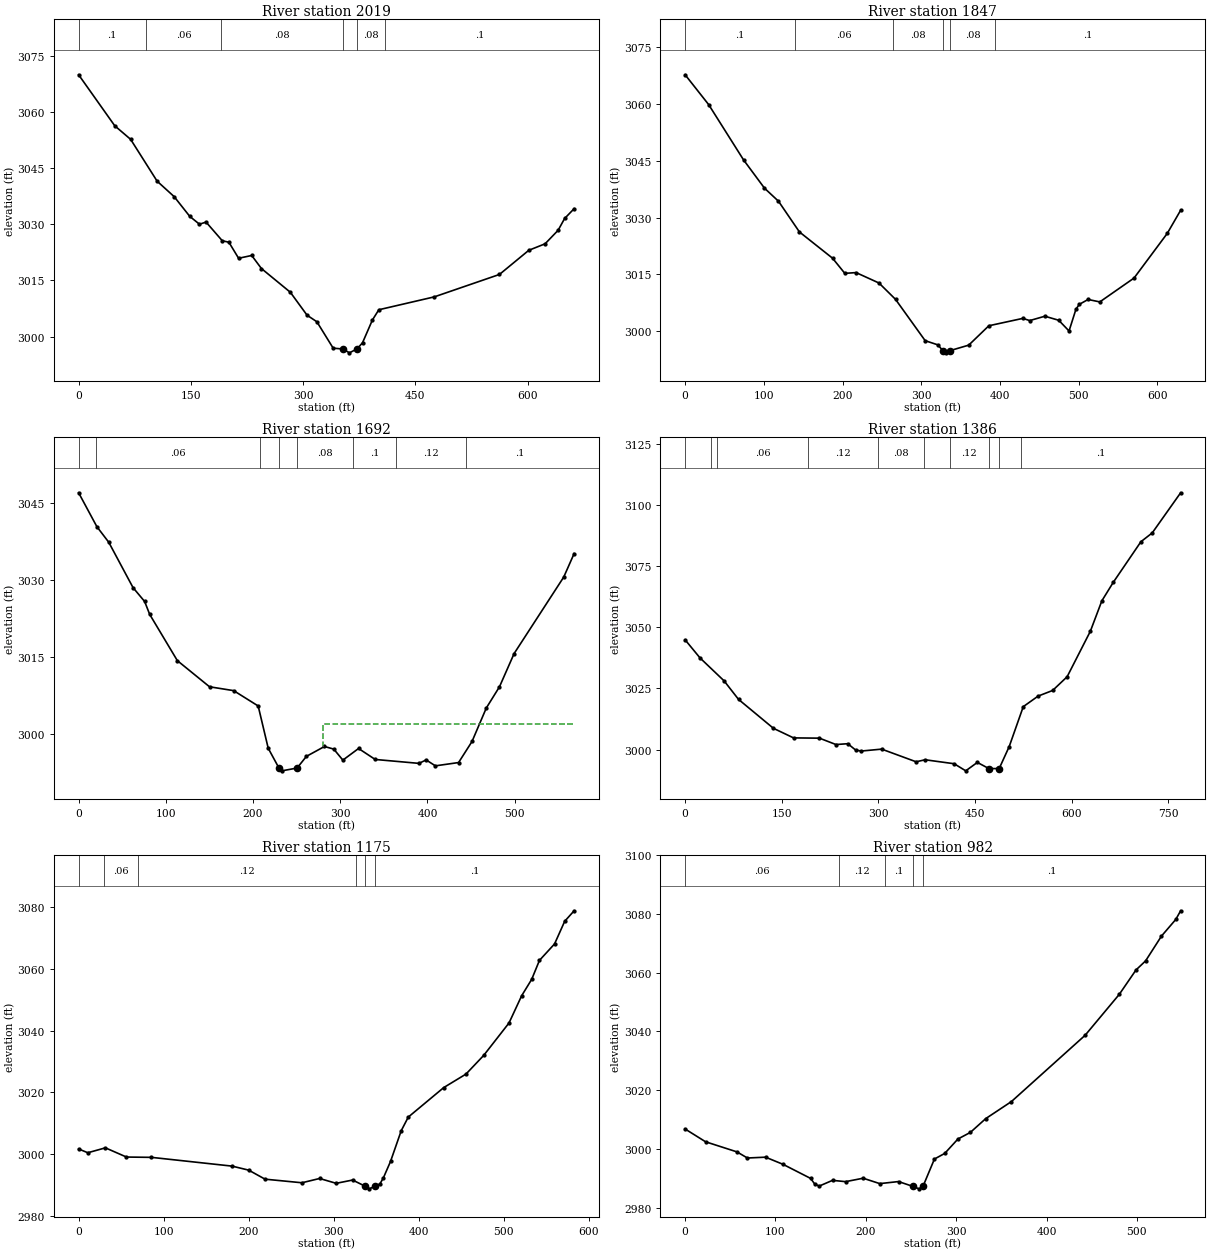
Type RM Length L Ch R = 1 ,2019    ,169.1,171.6,174.9
XS GIS Cut Line= 2
2348252.47344635715236.7411911152347644.58076335714974.169557746
#Sta/Elev= 30
       0 3069.94    48.3 3056.31    69.5 3052.69   104.9 3041.52   127.7 3037.38
   148.5 3032.12   161.5 3030.02   170.3 3030.59     192  3025.6   200.8 3025.21
   213.8 3020.92   231.3 3021.67   244.3 3018.18   282.9 3011.85   305.3 3005.71
   318.4 3003.96   340.2  2996.9   353.3 2996.69   361.9 2995.66   372.1 2996.72
   379.4 2998.35   392.6 3004.43   401.2 3007.17   475.3 3010.61   562.4  3016.6
   601.6 3023.05   623.4 3024.79   640.8  3028.4   649.5 3031.55   662.2 3034.17
#Mann= 6, -1 ,  0
       0     0.1       0      90    0.06       0     190    0.08       0
   353.3   0.045       0   372.1    0.08       0     410     0.1       0
Bank Sta=353.3,372.1
XS Rating Curve= 0 ,0
Exp/Cntr(USF)=0,0
Exp/Cntr=0.3,0.1

Type RM Length L Ch R = 1 ,1847    ,156.1,155.1,153.5
XS GIS Cut Line= 4
2348303.10166781715134.1437887212348118.90353917715045.850470858
2347943.83920202714887.531418138 2347769.6574822714813.282716988
#Sta/Elev= 30
       0 3067.73    29.9 3059.85    74.2 3045.26   100.8 3037.79   118.6 3034.34
   145.2 3026.23   187.3 3019.29   202.9 3015.29   217.2 3015.49   246.3 3012.74
   267.3 3008.43     305 2997.51   321.2  2996.4  327.342994.895   331.3  2994.3
   336.5 2994.88   360.3 2996.33   385.9 3001.45   429.1  3003.4   437.8 3002.82
   457.1 3003.97   474.7  3002.9   487.8 3000.07   496.5 3005.77   500.8  3007.1
     512 3008.39   526.9 3007.75   570.4 3014.05   612.6 3025.84   629.6 3031.95
#Mann= 6, -1 ,  0
       0     0.1       0     140    0.06       0  264.27    0.08       0
  327.34   0.045       0   336.5    0.08       0  394.27     0.1       0
Bank Sta=327.34,336.5
XS Rating Curve= 0 ,0
Exp/Cntr(USF)=0,0
Exp/Cntr=0.3,0.1

Type RM Length L Ch R = 1 ,1692    ,304,306.3,295.8
XS GIS Cut Line= 4
2348338.32213636714978.3557584062348184.08988773714889.743347785
2348098.14128521714826.7809994242347884.34867861714640.200140533
#Sta/Elev= 30
       0 3046.93    20.9 3040.35    34.5 3037.33    62.4  3028.5    75.7 3025.81
    81.5  3023.3   113.2 3014.32   150.1 3009.24   177.8 3008.49   205.9 3005.51
   217.4  2997.3   229.7 2993.46     233 2992.91  250.492993.453   261.2 2995.72
   281.9 2997.64   292.6 2997.13     303 2994.99     321 2997.25   340.1 2995.12
   390.3 2994.36   398.5 2995.03   409.1 2993.88   435.7 2994.52   451.1 2998.61
   467.5 3005.12   482.6 3009.24   499.4  3015.7   556.3 3030.56   568.2 3035.12
#Mann= 8, -1 ,  0
       0     0.1       0      20    0.06       0  207.88    0.08       0
   229.7   0.045       0  250.49    0.08       0  314.42     0.1       0
  364.42    0.12       0  444.42     0.1       0
#XS Ineff= 2 , 0
                          280.16         3001.98
Permanent Ineff=
       F       F
Bank Sta=229.7,250.49
XS Rating Curve= 0 ,0
Exp/Cntr(USF)=0,0
Exp/Cntr=0.3,0.1

Type RM Length L Ch R = 1 ,1386    ,203.8,210.5,215.5
XS GIS Cut Line= 3
2348406.91169669714894.9793021652348172.02458961714706.955987433
2347755.45999951714493.036623402
#Sta/Elev= 30
       0  3044.9    23.1  3037.5    60.5  3028.1    82.9 3020.52     137 3008.69
   168.3 3004.76   208.5 3004.65   234.1 3002.04   252.5 3002.38   264.8 2999.75
   273.6 2999.38   305.1 3000.16   358.5 2994.98   372.6  2995.8   417.6 2994.18
   435.6 2991.27   453.6 2994.72   471.6 2992.19   487.52992.198   503.1 3001.23
   524.9 3017.55     548 3021.88   570.5 3024.18     593  3029.8     629  3048.4
   646.9 3060.88   664.5 3068.41   707.5 3085.07   725.1 3088.69   769.2 3105.12
#Mann= 10, -1 ,  0
       0     0.1       0      40    0.12       0      50    0.06       0
     190    0.12       0     300    0.08       0  370.87     0.1       0
  410.87    0.12       0   471.6   0.045       0   487.5    0.12       0
  520.87     0.1       0
Bank Sta=471.6,487.5
XS Rating Curve= 0 ,0
Exp/Cntr(USF)=0,0
Exp/Cntr=0.3,0.1

Type RM Length L Ch R = 1 ,1175    ,193.7,192.6,185.3
XS GIS Cut Line= 4
2348402.57462125714695.8554262522348213.00377717714644.835393132
2348146.30491368714418.6634543132348011.61975367714350.925268195
#Sta/Elev= 30
       0 3001.77    10.8 3000.55    31.5 3002.13    56.3 2999.16    85.7 2999.06
   180.6 2996.23   200.1 2994.93   219.3 2992.02   262.7 2990.86   283.5 2992.24
     303 2990.68   322.3 2991.74   336.5 2989.82   341.9  2988.9  349.152989.806
   354.4 2990.47   358.6  2992.5   366.9 2997.73   379.5 3007.66   387.8 3012.06
   429.5 3021.58   455.7 3025.94   476.5 3031.96   506.3 3042.43   521.2 3051.23
     533 3056.52   542.1 3062.63   559.9 3067.95   571.8 3075.25   582.9 3078.64
#Mann= 6, -1 ,  0
       0    0.12       0      30    0.06       0      70    0.12       0
  326.32     0.1       0   336.5   0.045       0  349.15     0.1       0
Bank Sta=336.5,349.15
XS Rating Curve= 0 ,0
Exp/Cntr(USF)=0,0
Exp/Cntr=0.3,0.1

Type RM Length L Ch R = 1 ,982     ,152.9,153.1,150.4
XS GIS Cut Line= 3
2348469.23629732714655.8749727042348356.01773743714490.109626167
2348109.11914169714245.346792215
#Sta/Elev= 30
       0 3006.76    22.6 3002.41    57.4 2998.96    68.9 2996.88      89 2997.16
   108.3 2994.73   138.9 2989.92   143.7 2987.88   148.6 2987.34   163.1 2989.26
   177.6 2988.82     197 2989.99   215.4 2988.15   236.2 2988.85   252.2 2987.19
   258.9 2986.37  263.222987.194   275.9 2996.53   287.3 2998.44   301.9 3003.35
   315.7 3005.61   332.7 3010.31   361.1 3016.11   442.7 3038.71   480.5 3052.66
     499 3060.97   509.6 3064.06   527.2 3072.52     543 3078.18   548.4 3081.14
#Mann= 5, -1 ,  0
       0    0.06       0     170    0.12       0  220.74     0.1       0
   252.2   0.045       0  263.22     0.1       0
Bank Sta=252.2,263.22
XS Rating Curve= 0 ,0
Exp/Cntr(USF)=0,0
Exp/Cntr=0.3,0.1

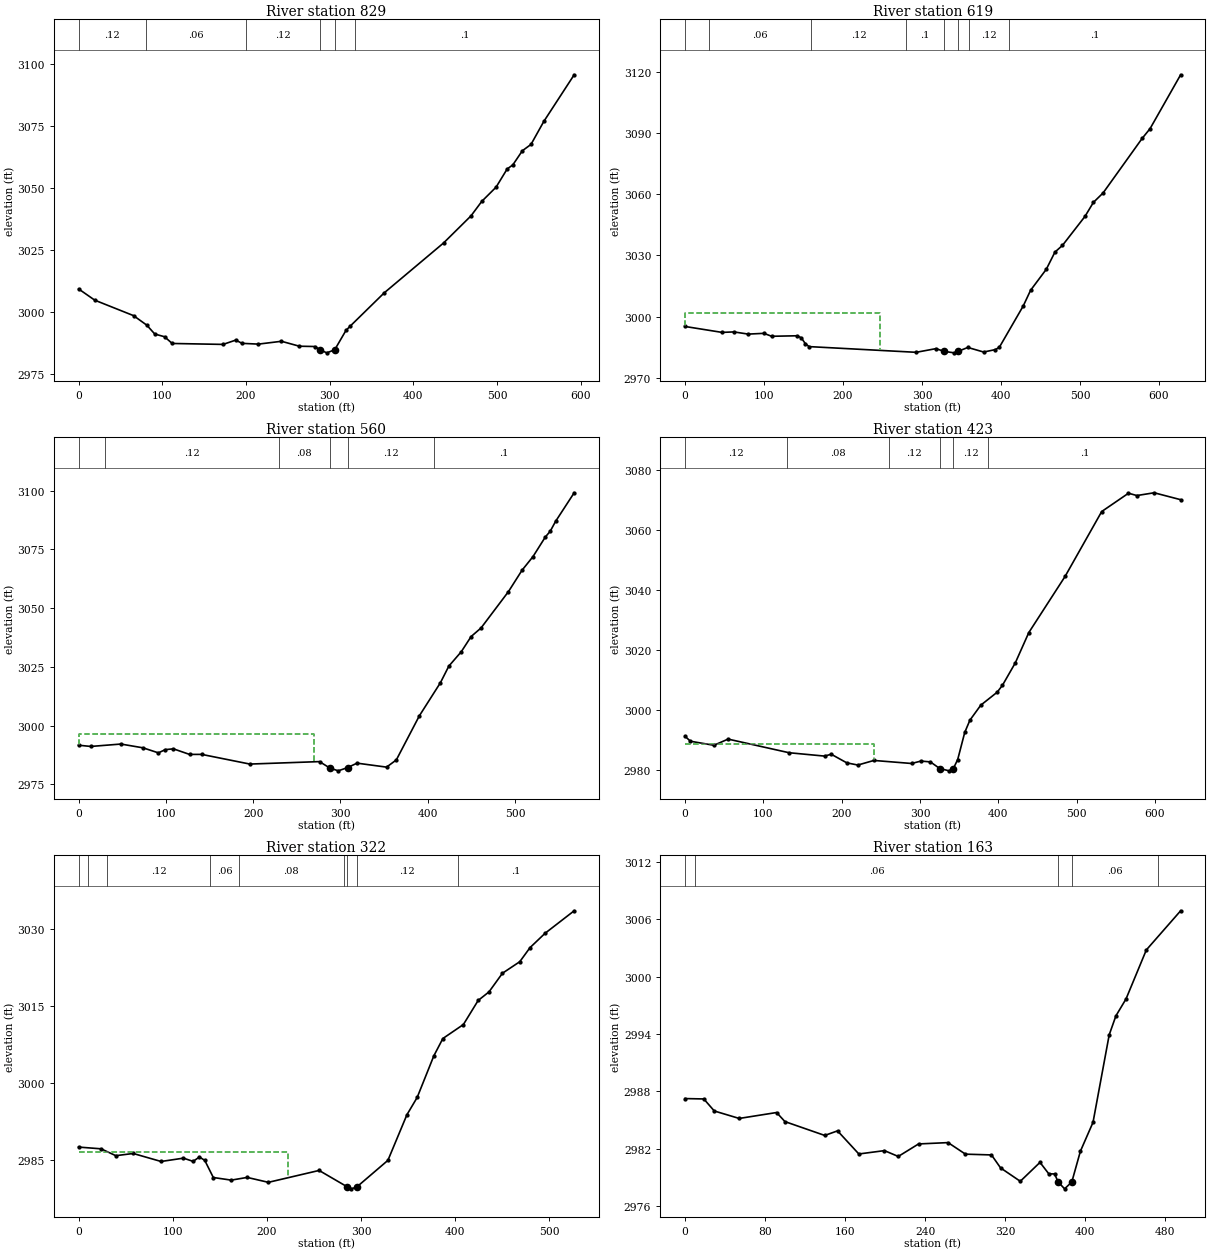
Type RM Length L Ch R = 1 ,829     ,210.6,210.5,210.4
XS GIS Cut Line= 2
 2348628.4357944714541.0170003462348160.96339032714177.535231038
#Sta/Elev= 30
       0 3009.32    19.3 3004.79    65.6 2998.56    81.4 2994.73      91 2991.14
   102.7 2990.04   111.8 2987.33   172.6 2986.95   187.8 2988.69   195.2 2987.38
   214.8 2987.07   242.4 2988.21   263.8 2986.22   282.3  2986.1  288.712984.748
   296.5 2983.55     306 2984.77   319.5  2992.6   324.6 2994.34   365.1 3007.72
   436.1 3027.86   468.9  3038.8   481.8 3044.65   498.9 3050.39   512.1 3057.71
   518.9 3059.37   530.3 3065.07   540.6 3067.62   555.9 3076.88   592.2 3095.71
#Mann= 6, -1 ,  0
       0    0.12       0      80    0.06       0     200    0.12       0
  288.71   0.045       0     306    0.12       0     330     0.1       0
Bank Sta=288.71,306
XS Rating Curve= 0 ,0
Exp/Cntr(USF)=0,0
Exp/Cntr=0.3,0.1

Type RM Length L Ch R = 1 ,619     ,59.7,58.6,57
XS GIS Cut Line= 2
2348793.41113838714397.4411505272348293.29487649714018.437252549
#Sta/Elev= 30
       0 2995.14    46.7 2992.25    61.8 2992.48    79.9 2991.41    99.8 2991.78
   109.6 2990.34   142.1 2990.59   147.1 2989.59   152.4 2986.65   157.1 2985.28
   292.6 2982.49   317.7 2984.29   327.8 2982.96   340.8 2982.23  345.612982.943
     358 2984.87     378 2982.63     393 2983.82     398    2985   428.2 3005.21
   437.5 3012.88   457.4 3023.18   468.3 3031.57   477.9 3034.89   506.4 3049.08
     517 3055.92   529.3 3060.56   578.7 3087.25   588.8 3092.07   627.5 3118.45
#Mann= 8, -1 ,  0
       0     0.1       0      30    0.06       0     160    0.12       0
     280     0.1       0   327.8   0.045       0  345.61     0.1       0
     360    0.12       0     410     0.1       0
#XS Ineff= 2 , 0
          247.31 3001.63
Permanent Ineff=
       F       F
Bank Sta=327.8,345.61
XS Rating Curve= 0 ,0
Exp/Cntr(USF)=0,0
Exp/Cntr=0.3,0.1

Type RM Length L Ch R = 1 ,560     ,133.8,136.8,138.6
XS GIS Cut Line= 4
2348818.05286373 714296.203374932348697.47773288714226.086315142
2348482.53945615714103.545285418 2348361.9643253713968.634464024
#Sta/Elev= 30
       0 2991.68      14 2991.16    48.4 2992.18    73.8 2990.57    91.4 2988.43
    99.3 2989.81   108.6 2990.14   127.1 2987.77     141 2987.78   196.2 2983.66
     276 2984.71   287.7    2982   297.5 2980.78   308.3 2982.19     319 2984.05
   352.8 2982.36     364 2985.41   390.4 3004.19   414.5 3018.25   424.2 3025.35
   438.4 3031.44   449.7 3037.92   461.1 3041.58   492.5 3057.05   508.1 3066.16
   520.6 3071.93   534.7 3080.25   540.4 3082.76   546.5 3086.93   567.8  3099.1
#Mann= 6, -1 ,  0
       0    0.06       0      30    0.12       0  229.48    0.08       0
   287.7   0.045       0   308.3    0.12       0   406.9     0.1       0
#XS Ineff= 2 , 0
          269.61 2996.25
Permanent Ineff=
       F       F
Bank Sta=287.7,308.3
XS Rating Curve= 0 ,0
Exp/Cntr(USF)=0,0
Exp/Cntr=0.3,0.1

Type RM Length L Ch R = 1 ,423     ,99.6,102,104.4
XS GIS Cut Line= 3
2348828.69347393714276.1854241312348590.94907173714009.719936313
2348391.77308199713819.114387245
#Sta/Elev= 30
       0 2991.33     6.8  2989.7    36.8 2988.35    54.9 2990.41   132.8 2985.87
   178.1 2984.75   186.6 2985.37   206.5  2982.5   220.6 2981.77   241.1  2983.3
   289.2 2982.29   301.2 2983.09   313.2 2982.82   325.2 2980.61   337.2 2979.84
   342.5 2980.58   348.1 2983.59   357.1 2992.63   363.7 2996.71   377.6 3001.71
   398.4    3006   405.2  3008.3   421.7 3015.81   438.9 3025.88   485.2 3044.57
     532 3066.19   566.2 3072.29   576.9 3071.52     599 3072.44   632.8 3070.14
#Mann= 6, -1 ,  0
       0    0.12       0     130    0.08       0     260    0.12       0
   325.2   0.045       0   342.5    0.12       0  387.11     0.1       0
#XS Ineff= 2 , 0
          241.34 2988.65
Permanent Ineff=
       F       F
Bank Sta=325.2,342.5
XS Rating Curve= 0 ,0
Exp/Cntr(USF)=0,0
Exp/Cntr=0.3,0.1

Type RM Length L Ch R = 1 ,322     ,160.3,158.5,155.1
XS GIS Cut Line= 4
2348883.21216156714186.0432275822348704.48428881714008.490784248
2348679.40741447713942.3894993132348529.76522402 713803.90949613
#Sta/Elev= 30
       0 2987.43    23.9 2987.09    39.5 2985.75      58 2986.18    87.6 2984.62
   111.4 2985.27   121.6 2984.64   128.3 2985.49     134 2984.84   143.1 2981.49
   162.2 2980.98   179.1 2981.51   201.6 2980.55   255.5 2982.87   285.4 2979.67
   289.7 2979.28  295.592979.654   328.6 2984.84   348.8 2993.74   359.7 2997.12
   377.4 3005.24     387 3008.62   408.8 3011.35   424.5 3016.05     436 3017.72
   450.3 3021.36   468.7 3023.61   479.6 3026.36   495.6 3029.16   526.5 3033.55
#Mann= 9, -1 ,  0
       0    0.12       0      10    0.06       0      30    0.12       0
     140    0.06       0     170    0.08       0  281.93    0.12       0
   285.4   0.045       0  295.59    0.12       0  402.63     0.1       0
#XS Ineff= 2 , 0
          222.88 2986.54
Permanent Ineff=
       F       F
Bank Sta=285.4,295.59
XS Rating Curve= 0 ,0
Exp/Cntr(USF)=0,0
Exp/Cntr=0.3,0.1

Type RM Length L Ch R = 1 ,163     ,,,
XS GIS Cut Line= 4
2348914.62383159714192.2199823462348809.91304934713907.450788993
2348729.28090759713849.6874045142348638.70661783 713829.33632534
#Sta/Elev= 30
       0 2987.25    18.7 2987.21    29.2 2985.95    54.1 2985.17    91.5 2985.79
    99.8 2984.84   139.6 2983.39   152.4 2983.87   173.7 2981.45   199.3  2981.8
   213.1 2981.19   233.4  2982.5   262.9 2982.64   280.3 2981.43   306.3 2981.35
   315.4 2979.99   335.1 2978.59   354.8 2980.57   363.6 2979.37   369.4 2979.36
  372.912978.526   379.4  2977.8   386.6 2978.52   395.2 2981.74   407.8 2984.76
     424 2993.93   430.7 2995.91   440.8 2997.68   461.1 3002.81   495.4 3006.91
#Mann= 5, -1 ,  0
       0    0.12       0      10    0.06       0  372.91   0.045       0
   386.6    0.06       0   472.6     0.1       0
Bank Sta=372.91,386.6
XS Rating Curve= 0 ,0
Exp/Cntr(USF)=0,0
Exp/Cntr=0.3,0.1
LCMann Table=0

Chan Stop Cuts=-1
Use User Specified Reach Order=0
Composite Channel Slope=5